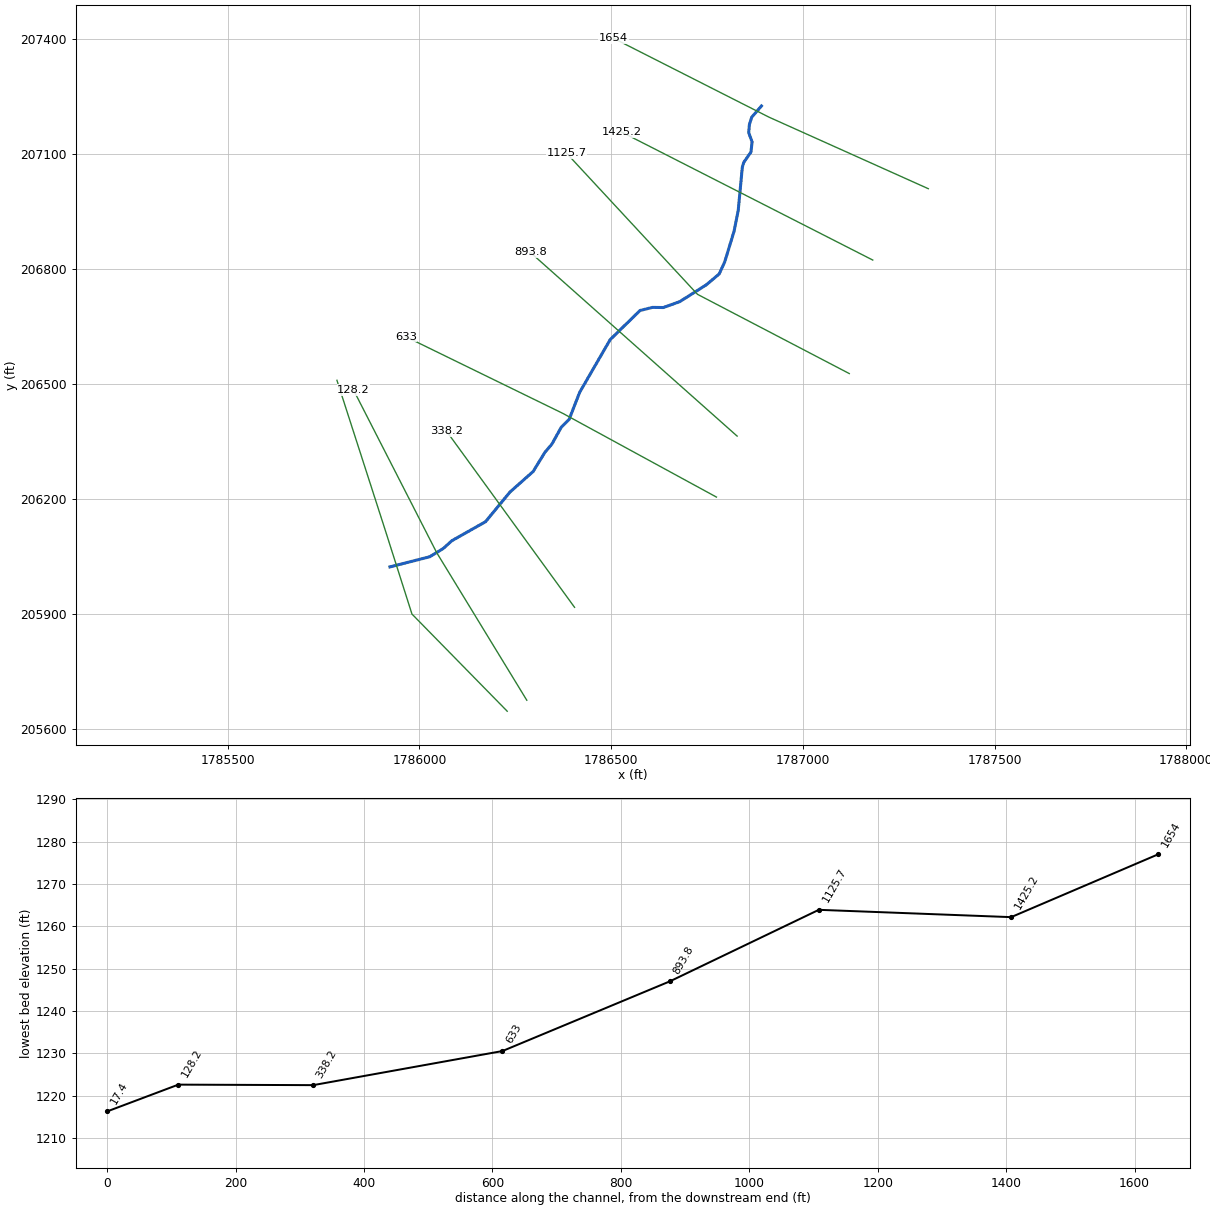
--- ShopBr.prj (project) ---

Proj Title=ShopBr
Current Plan=p01
Default Exp/Contr=0,0
English Units
Geom File=g01
Flow File=f01
Plan File=p01
BEGIN DESCRIPTION:
END DESCRIPTION:
DSS Export Rating Curves= 0
DSS Export Rating Curve Sorted= 0
DSS Export Volume Flow Curves= 0
DXF OffsetX= 0
DXF OffsetY= 0
DXF ScaleX= 0
DXF ScaleY= 0

--- ShopBr.p01 (plan) ---

Plan Title=Floodplain
Program Version=4.00
Geom File=g01
Flow File=f01
K Sum by GR=0
Std Step Tol=0.01
Critical Tol=0.01
Num of Std Step Trials=20
Max Error Tol=0.3
Flow Tol Ratio=0.001
Split Flow NTrial=30
Split Flow Tol=0.02
Split Flow Ratio=0.02
Log Output Level=0
Friction Slope Method=1
Unsteady Friction Slope Method=2
Unsteady Bridges Friction Slope Method=1
Global Log Level=0
CheckData=False
Run HTab=0
Run UNet=0
Run PostProcess=0
UNET Theta=0
UNET Theta Warmup=0
UNET ZTol=0
UNET ZSATol=0
UNET MxIter=0
UNET MaxInSteps=0
UNET DtIC=0
UNET DtMin=0
UNET MaxCRTS=0
UNET WFStab=0
UNET SFStab=0
UNET WFX=0
UNET SFX=0
UNET DSS MLevel=0
UNET DZMax Abort=0
UNET Convert EG Bridges=0
UNET Use Existing IB Tables=0
UNET Froude Limit=0
UNET Froude Power=0
Write IC File=0
Echo Input=False
Echo Output=False
Write Detailed=0

--- ShopBr.f01 (steady flow) ---

Flow Title=NFF Regression Equation
Program Version=4.00
Number of Profiles=1
Profile Names=P100yr
River Rch & RM=ShopBr,Main      ,1654
603.6610
River Rch & RM=ShopBr,Main      ,1125.7
614.7118
River Rch & RM=ShopBr,Main      ,633
691.2839
River Rch & RM=ShopBr,Main      ,128.2
702.8905
Boundary for River Rch & Prof#=ShopBr,Main      ,1
Up Type=0
Dn Type=3
Dn Slope=0.030979

--- ShopBr.g01 (geometry) ---

Geom Title=USGS 10m DEM
Program Version=4.00

River Reach=ShopBr     ,Main
Reach XY= 30
     1786892.114      207226.083     1786866.695      207196.754
     1786860.829      207178.178     1786858.874      207156.670
     1786867.673      207132.228     1786864.739      207105.832
     1786846.253      207079.524     1786842.253      207066.725
     1786831.499      206953.317     1786820.745      206899.546
     1786796.304      206819.378     1786781.813      206787.839
     1786748.398      206759.741     1786678.985      206715.746
     1786636.161      206700.429     1786607.946      206700.804
     1786575.426      206692.674     1786497.648      206616.805
     1786417.950      206479.153     1786390.575      206408.762
     1786370.045      206388.231     1786345.603      206344.236
     1786327.282      206322.731     1786296.720      206272.867
     1786236.106      206219.096     1786172.558      206141.861
     1786084.746      206092.312     1786062.430      206072.106
     1786026.940      206050.444     1785923.258      206024.023

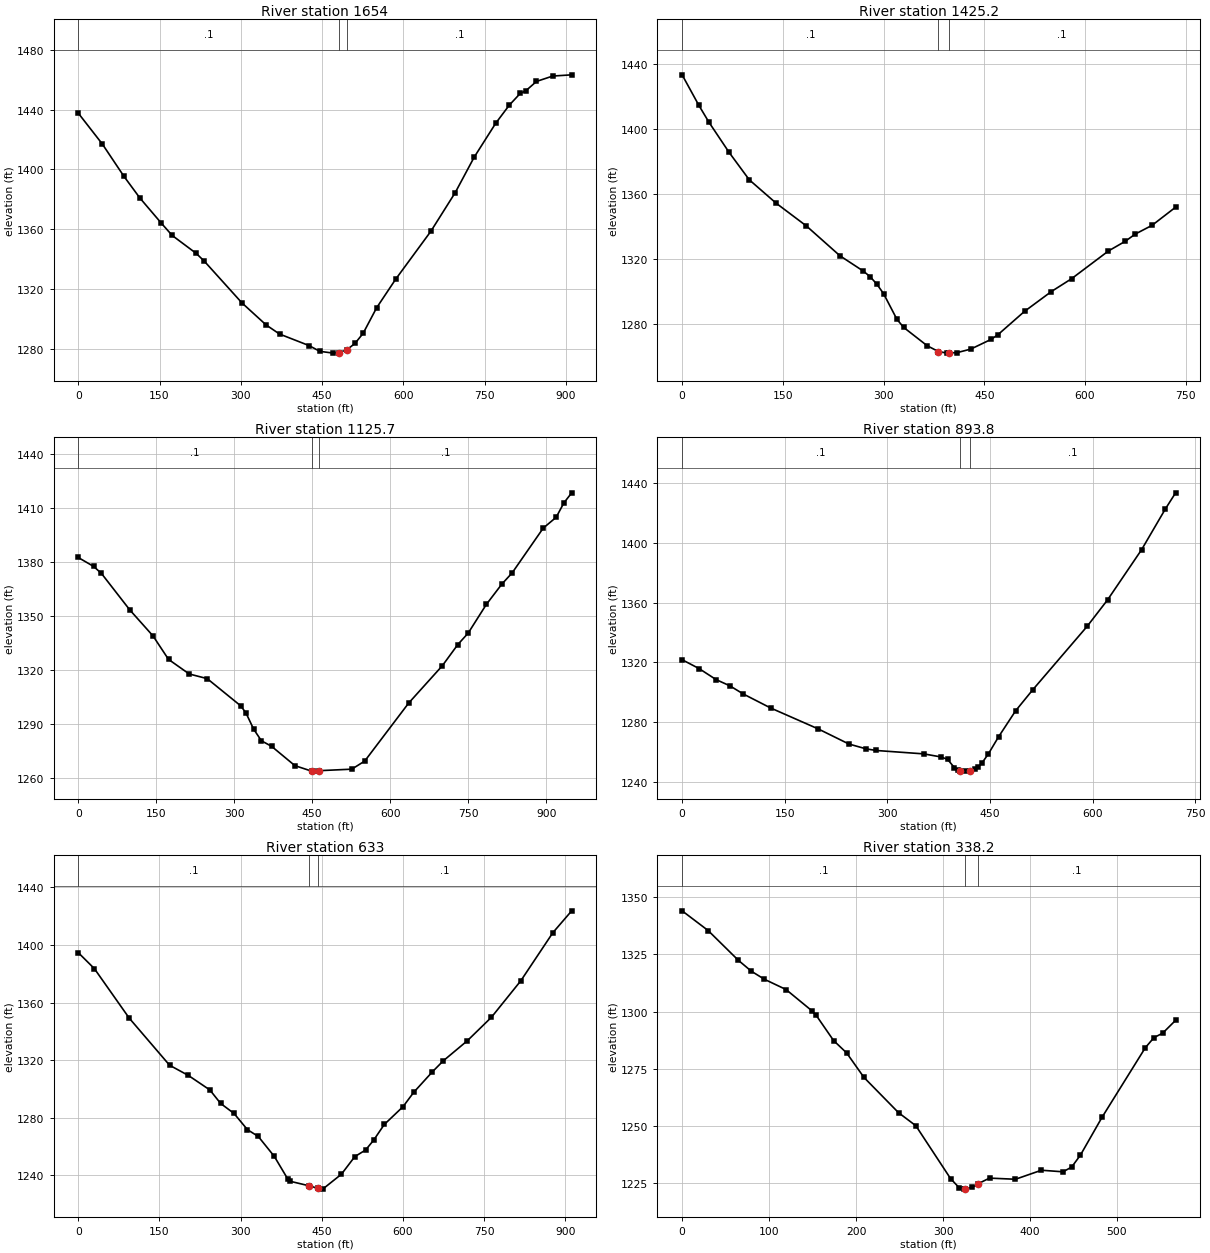
Type RM Length L Ch R = 1 ,1654,233.5,228.8,238.2
XS GIS Cut Line= 3
     1787327.282      207010.317     1786911.649      207196.968
     1786505.964      207402.747
#Sta/Elev= 30
       0 1437.66    44.6 1416.90    84.2 1395.41   113.9 1380.77   153.5 1363.92
   173.3 1355.79   217.9 1343.70   232.8 1338.48   302.1 1310.62   346.7 1295.87
   371.4 1289.79   425.9 1282.06   445.7 1278.22   470.6 1277.01   480.9 1277.29
   495.9 1279.34   510.6 1283.50   525.6 1290.21   550.6 1307.37   585.6 1326.42
   650.6 1358.53   695.6 1384.44   730.6 1408.17   770.5 1430.96   795.5 1443.03
   815.5 1450.81   825.5 1452.48   845.5 1458.84   875.5 1462.44   910.5 1463.26
#Mann= 3 , 0 , 0
       0     0.1       0   480.9   0.045       0   495.9     0.1       0
Bank Sta=   480.9,   495.9
Exp/Cntr=0.3,0.1

Type RM Length L Ch R = 1 ,1425.2,301.7,299.5,292.2
XS GIS Cut Line= 2
     1787182.362      206824.261     1786527.589      207157.919
#Sta/Elev= 30
       0 1433.59    25.0 1414.74    40.0 1404.36    70.0 1385.80   100.0 1368.94
   140.0 1354.53   185.0 1340.53   235.0 1322.15   270.0 1312.65   280.0 1309.26
   290.0 1304.64   300.0 1298.82   320.0 1282.91   330.0 1278.00   364.9 1266.74
   381.7 1263.14   394.9 1262.17   396.7 1262.23   409.9 1262.52   429.9 1264.66
   459.9 1270.60   469.9 1273.37   509.9 1287.89   549.9 1300.11   579.9 1307.98
   634.9 1325.10   659.9 1331.06   674.9 1335.52   699.9 1340.90   734.9 1352.06
#Mann= 3 , 0 , 0
       0     0.1       0   381.7   0.045       0   396.7     0.1       0
Bank Sta=   381.7,   396.7
Exp/Cntr=0.3,0.1

Type RM Length L Ch R = 1 ,1125.7,234.9,231.8,234
XS GIS Cut Line= 3
     1787121.133      206528.238     1786725.232      206734.922
     1786383.422      207103.364
#Sta/Elev= 30
       0 1382.49    29.8 1377.50    44.7 1373.62    99.2 1353.39   143.9 1338.94
   173.7 1325.93   213.4 1317.84   248.1 1315.24   312.6 1300.13   322.6 1296.22
   337.4 1287.22   352.3 1280.77   372.2 1277.61   416.8 1266.94   448.8 1263.91
   451.6 1263.90   463.8 1264.15   526.2 1264.99   551.1 1269.49   635.7 1301.71
   700.4 1322.42   730.2 1334.18   750.1 1340.53   785.0 1356.43   814.8 1367.70
   834.7 1373.96   894.4 1398.78   919.3 1404.80   934.2 1412.82   949.2 1418.38
#Mann= 3 , 0 , 0
       0     0.1       0   448.8   0.045       0   463.8     0.1       0
Bank Sta=   448.8,   463.8
Exp/Cntr=0.3,0.1

Type RM Length L Ch R = 1 ,893.8,255.6,260.9,266.1
XS GIS Cut Line= 2
     1786828.634      206365.167     1786289.261      206844.331
#Sta/Elev= 30
       0 1321.67    24.9 1315.70    49.8 1308.31    69.7 1304.20    89.6 1298.66
   129.4 1289.32   199.0 1275.29   243.8 1265.18   268.7 1261.96   283.6 1260.84
   353.3 1258.56   378.2 1256.52   388.1 1254.90   398.0 1249.38   403.0 1247.52
   405.8 1247.25   413.0 1247.00   420.8 1247.41   427.9 1248.25   432.9 1249.73
   437.9 1252.12   447.8 1258.59   462.7 1270.02   487.6 1287.43   512.5 1301.43
   592.1 1343.99   622.0 1361.76   671.7 1395.35   706.5 1422.68   721.5 1433.51
#Mann= 3 , 0 , 0
       0     0.1       0   405.8   0.045       0   420.8     0.1       0
Bank Sta=   405.8,   420.8
Exp/Cntr=0.3,0.1

Type RM Length L Ch R = 1 ,633,304.9,294.7,284.5
XS GIS Cut Line= 3
     1786774.740      206206.123     1786373.751      206424.598
     1785964.862      206624.211
#Sta/Elev= 30
       0 1394.66    29.8 1383.55    94.3 1349.14   168.8 1316.49   203.5 1309.40
   243.2 1299.34   263.1 1289.98   287.9 1283.00   312.7 1271.76   332.6 1267.08
   362.3 1253.21   387.2 1237.48   392.1 1235.91   427.2 1232.75   442.2 1231.10
   451.7 1230.51   486.3 1240.88   511.0 1253.08   530.8 1257.63   545.7 1264.43
   565.4 1275.36   600.1 1287.74   619.8 1297.68   654.5 1311.99   674.3 1319.50
   718.8 1333.46   763.3 1349.74   817.7 1375.11   877.0 1408.53   911.7 1423.64
#Mann= 3 , 0 , 0
       0     0.1       0   427.2   0.045       0   442.2     0.1       0
Bank Sta=   427.2,   442.2
Exp/Cntr=0.3,0.1

Type RM Length L Ch R = 1 ,338.2,211.8,210,206.6
XS GIS Cut Line= 2
     1786404.662      205918.616     1786071.003      206377.711
#Sta/Elev= 30
       0 1343.96    29.9 1335.36    64.7 1322.35    79.6 1317.60    94.6 1314.08
   119.5 1309.60   149.4 1300.27   154.3 1298.27   174.2 1287.32   189.2 1281.92
   209.1 1271.23   248.9 1255.82   268.8 1250.12   308.7 1227.06   318.6 1223.06
   323.6 1222.45   325.2 1222.51   333.6 1223.20   340.2 1224.77   353.5 1227.26
   383.3 1226.76   413.2 1230.70   438.1 1230.01   448.0 1232.11   458.0 1237.27
   482.9 1253.82   532.7 1284.21   542.6 1288.60   552.6 1290.54   567.5 1296.15
#Mann= 3 , 0 , 0
       0     0.1       0   325.2   0.045       0   340.2     0.1       0
Bank Sta=   325.2,   340.2
Exp/Cntr=0.3,0.1

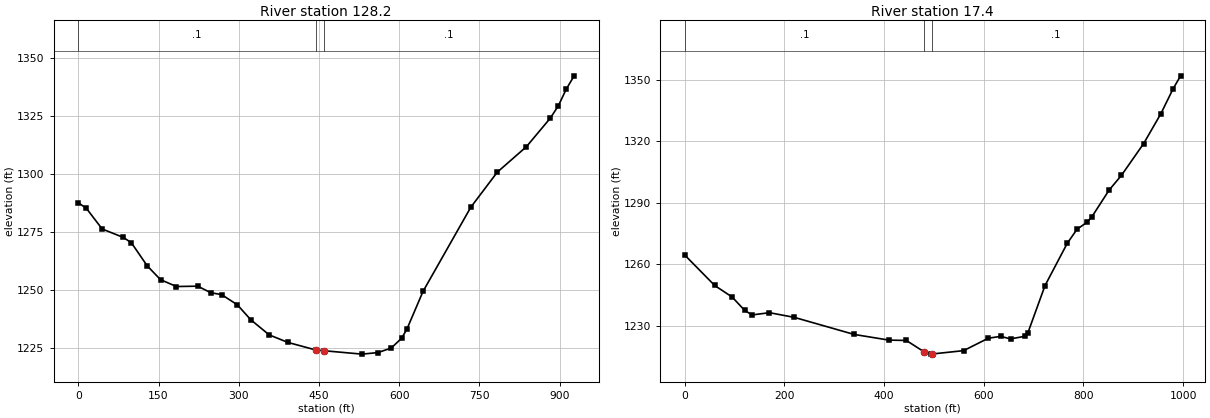
Type RM Length L Ch R = 1 ,128.2,116.2,110.8,107.1
XS GIS Cut Line= 3
     1786280.124      205676.298     1786045.015      206061.476
     1785828.244      206485.450
#Sta/Elev= 30
       0 1287.78    14.9 1285.43    44.6 1276.49    84.3 1272.84    99.2 1270.56
   128.9 1260.60   153.7 1254.66   183.5 1251.70   223.2 1251.85   248.0 1249.01
   267.8 1248.23   297.5 1243.82   322.3 1237.43   357.0 1230.86   391.8 1227.63
   443.8 1224.38   458.8 1224.05   530.6 1222.57   560.4 1223.24   585.2 1225.19
   605.0 1229.48   615.0 1233.56   644.7 1249.59   734.0 1285.84   783.6 1300.97
   838.2 1311.98   882.8 1324.26   897.7 1329.52   912.6 1336.75   927.4 1342.49
#Mann= 3 , 0 , 0
       0     0.1       0   443.8   0.045       0   458.8     0.1       0
Bank Sta=   443.8,   458.8
Exp/Cntr=0.3,0.1

Type RM Length L Ch R = 1 ,17.4,19.1,17.4,15.7
XS GIS Cut Line= 4
     1786229.052      205647.676     1785980.690      205901.056
     1785907.937      206129.348     1785785.011      206510.672
#Sta/Elev= 30
       0 1264.56    60.0 1249.73    95.0 1244.11   119.9 1237.65   134.9 1235.36
   169.9 1236.46   219.9 1234.17   339.8 1225.85   409.7 1223.08   444.6 1222.91
   480.6 1217.30   494.6 1216.24   495.6 1216.29   559.5 1217.94   609.2 1224.01
   634.0 1224.90   653.8 1223.67   683.4 1224.98   688.4 1226.52   723.0 1249.72
   767.5 1270.28   787.3 1277.21   807.1 1280.54   817.0 1283.26   851.6 1296.29
   876.4 1303.50   920.9 1318.99   955.5 1333.58   980.2 1345.82   995.1 1352.04
#Mann= 3 , 0 , 0
       0     0.1       0   480.6   0.045       0   495.6     0.1       0
Bank Sta=   480.6,   495.6
Exp/Cntr=0.3,0.1